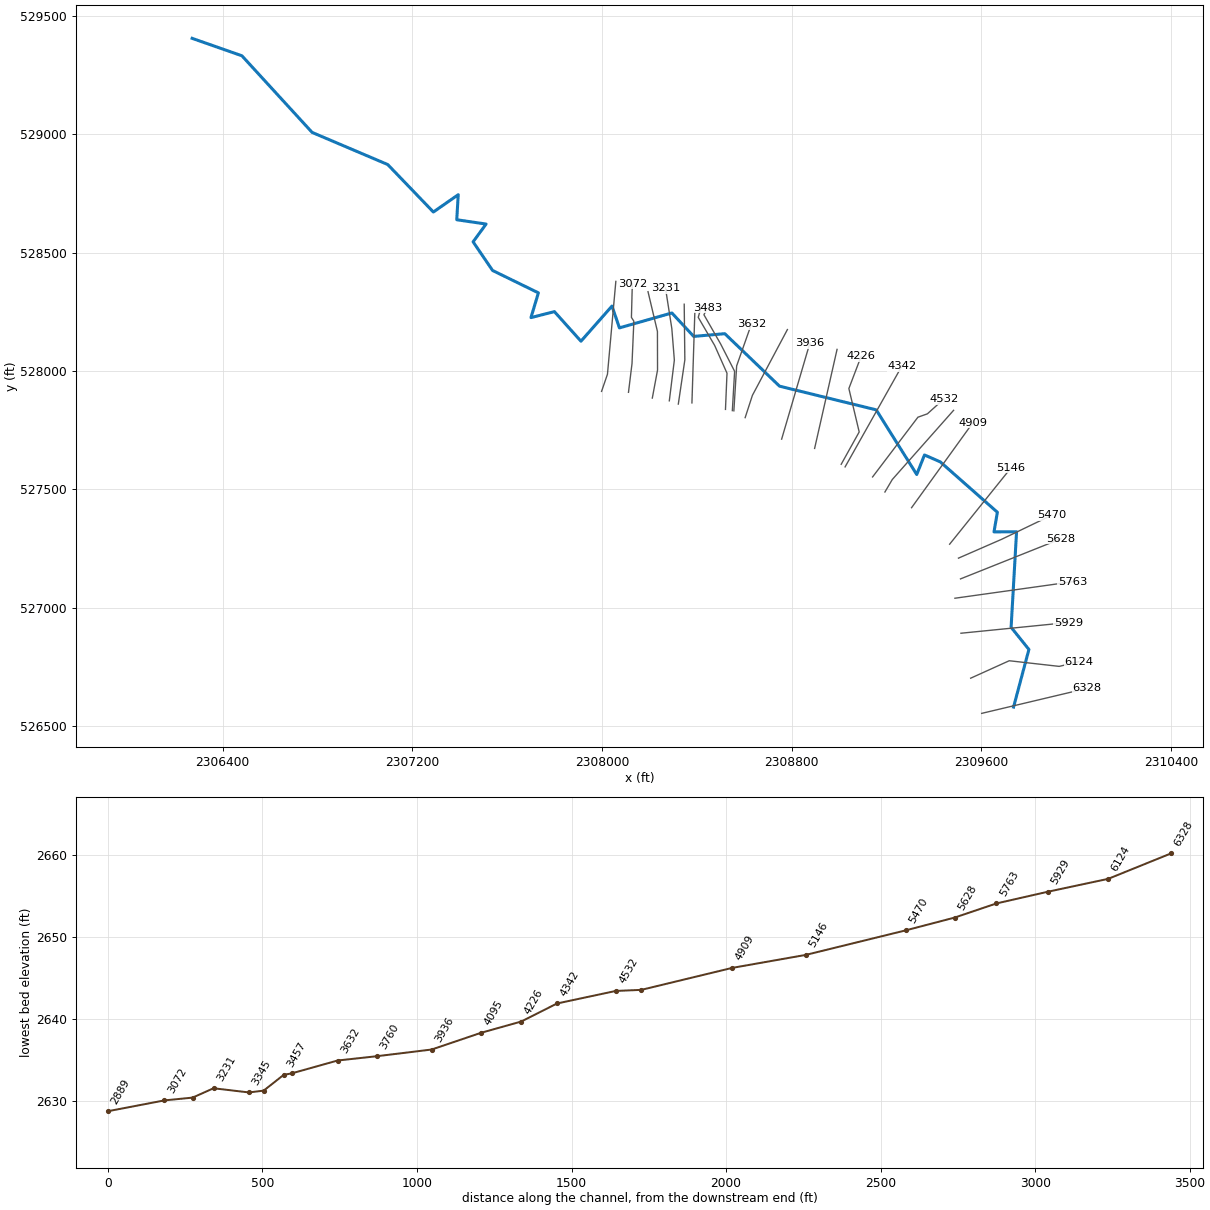
--- MLLSTNRN.prj (project) ---

Proj Title=MLLSTNRN
Current Plan=p01
Default Exp/Contr=0,0
English Units
Geom File=g01
Flow File=f01
Plan File=p01
Background Map Layer=Inundation Boundary (01pct Value_0)
BEGIN DESCRIPTION:
----------MODEL BY WOOD PLC 2021----------
Stream Name: Millstone Run
Flood Zone: Enhanced Approximate
Pocahontas County, WV
HEC-RAS Version: RAS 6.1
Vertical Datum: NAVD88
Projection: NAD 1983 StatePlane West Virginia S FIPS 4702 (US Feet)
Terrain: 1-meter LIDAR (FEMA Region III 3DEP collected 2016-2018)
Land Use: 2019 NLCD
Hydrologic Method:
WV SIR2010-5033 regression equations
END DESCRIPTION:
DSS Export Rating Curves= 0
DSS Export Rating Curve Sorted= 0
DSS Export Volume Flow Curves= 0
DXF OffsetX= 0
DXF OffsetY= 0
DXF ScaleX= 0
DXF ScaleY= 0

--- MLLSTNRN.p01 (plan) ---

Plan Title=Floodplain
Program Version=6.10
Short Identifier=Floodplain
Geom File=g01
Flow File=f01
Subcritical Flow
K Sum by GR= 0
Std Step Tol= 0.01
Critical Tol= 0.01
Num of Std Step Trials= 20
Max Error Tol= 0.3
Flow Tol Ratio= 0.001
Split Flow NTrial= 30
Split Flow Tol= 0.02
Split Flow Ratio= 0.02
Log Output Level= 0
Friction Slope Method= 1
Unsteady Friction Slope Method= 2
Unsteady Bridges Friction Slope Method= 1
Parabolic Critical Depth
Global Vel Dist= 0 , 0 , 0
Global Log Level= 0
CheckData=True
Encroach Param=-1 ,0,0, 0
Mapping Interval=1HOUR
Computation Time Step Use Courant=        0
Computation Time Step Use Time Series=    0
Computation Time Step Count To Double=0
Computation Time Step Max Doubling=0
Computation Time Step Max Halving=0
Computation Time Step Residence Courant=0
Run HTab= 0
Run UNet= 0
Run Sediment= 0
Run PostProcess= 0
Run WQNet= 0
Run RASMapper=-1
UNET Theta= 0
UNET Theta Warmup= 0
UNET ZTol= 0
UNET ZSATol= 0
UNET MxIter= 0
UNET Max Iter WO Improvement= 0
UNET MaxInSteps= 0
UNET DtIC= 0
UNET DtMin= 0
UNET MaxCRTS= 0
UNET WFStab= 0
UNET SFStab= 0
UNET WFX= 1
UNET SFX= 1
UNET Gravity=32.174
UNET 1D Methodology=Finite Difference
UNET DSS MLevel= 1
UNET Pardiso=0
UNET DZMax Abort= 0
UNET Use Existing IB Tables= 0
UNET Froude Reduction=False
UNET Froude Limit= 0
UNET Froude Power= 0
UNET D1 Cores= 0
UNET WindReference=Eulerian
UNET WindDragFormulation=Hsu (1988)
UNET D2 Coriolis=0
UNET D2 Cores= 0
UNET D2 Theta= 1
UNET D2 Theta Warmup= 1
UNET D2 Z Tol= 0.01
UNET D2 Volume Tol= 0.01
UNET D2 Max Iterations= 20
UNET D2 Equation= 0
UNET D2 RampUpFraction=0.1
UNET D2 TimeSlices= 1
UNET D2 Turbulence Formulation=Non-Conservative (original)
UNET D2 Eddy Viscosity=0.3
UNET D2 Transverse Eddy Viscosity=0.1
UNET D2 Smagorinsky Mixing=0
UNET D2 BCVolumeCheck=0
UNET D2 Cores=0
UNET D2 SolverType=PARDISO (Direct)
UNET D2 Minimum Iterations= 2147483647
UNET D2 Maximum Iterations= 2147483647
UNET D2 Restart Number= 10
UNET D2 Relaxation Coeff=1.3
UNET D2 SOR Precondition Iterations= 10
UNET D2 ILUT Maximum Fill= 8
UNET D2 ILUT Tolerance=1E-08
UNET D1D2 MaxIter= 0
UNET D1D2 ZTol=0.01
UNET D1D2 QTol=0.1
UNET D1D2 MinQTol=1
Write IC File= 0
Write IC File at Fixed DateTime=0
Write IC File at Sim End=0
Echo Input=False
Echo Parameters=False
Echo Output=False
Write Detailed= 0
HDF Write Warmup=0
HDF Write Time Slices=0
HDF Flush=0
HDF Compression= 1
HDF Chunk Size= 1
HDF Spatial Parts= 1
HDF Use Max Rows=0
HDF Fixed Rows= 1
Calibration Method= 0
Calibration Iterations= 20
Calibration Max Change=0.05
Calibration Tolerance=0.2
Calibration Maximum=1.5
Calibration Minimum=0.5
Calibration Optimization Method= 1
WQ AD Non Conservative
WQ ULTIMATE=-1
WQ Max Comp Step=1HOUR
WQ Output Interval=15MIN
WQ Output Selected Increments= 0
WQ Output face flow=0
WQ Output face velocity=0
WQ Output face area=0
WQ Output face dispersion=0
WQ Output cell volume=0
WQ Output cell surface area=0
WQ Output cell continuity=0
WQ Output cumulative cell continuity=0
WQ Output face conc=0
WQ Output face dconc_dx=0
WQ Output face courant=0
WQ Output face peclet=0
WQ Output face adv mass=0
WQ Output face disp mass=0
WQ Output cell mass=0
WQ Output cell source sink temp=0
WQ Output nsm pathways=0
WQ Output nsm derived pathways=0
WQ Create Restart=0
WQ Fixed Restart=0
WQ System Summary=0
WQ Write To DSS=0
Sorting and Armoring Iterations= 10
XS Update Threshold= 0.02
Bed Roughness Predictor= 0
Hydraulics Update Threshold= 0.02
Energy Slope Method= 1
Volume Change Method= 1
Sediment Retention Method= 0
Sediment TS Multiplier= 1
Warm Up Method= 0
XS Weighting Method= 0
Number of US Weighted Cross Sections= 1
Number of DS Weighted Cross Sections= 1
Upstream XS Weight=0
Main XS Weight=1
Downstream XS Weight=0
Number of DS XS's Weighted with US Boundary= 1
Upstream Boundary Weight= 1
Weight of XSs Associated with US Boundary= 0
Number of US XS's Weighted with DS Boundary= 1
Downstream Boundary Weight= 0.5
Weight of XSs Associated with DS Boundary= 0.5
Percentile Method= 0
Sediment Output Level= 3
Mass or Volume Output= 0
Output Increment Type= 1
Profile and TS Output Increment= 1
Transport Output Increment 1
XS Output Flag= 0
XS Output Increment= 10
Read HDF5 Sediment Hotstart= 0
Sediment Hotstart Type= 0
Write Gradation File= 0
Read Gradation Hotstart= 0
Write HDF5 File= 1
Write Binary Output= 1
Write DSS Sediment File= 0
DSS Sediment Output Type= 1
SV Curve= 0
Specific Gage Flag= 0
Subcell Erosion Methods= 0
Subcell Deposition Methods= 0
Advection Scheme= 1
Matrix Solver= 0
Implicit Weighting Factor= 1
Maximum Outer Loop Convergence Iterations= 5
Convergence Maximum Absolute= 0.001
Convergence RMSE= 0.0001
Grain Fractions Max Abs Error= 0.001
Max Subgrid Regions= 1
Max Subgrid Length Scale= 3.402823E+38
Initial Layer Thickness= 3.402823E+38
Min Layer Thickness= 3.402823E+38
Max Layer Thickness= 3.402823E+38
Number of Layers= 5

--- MLLSTNRN.f01 (steady flow) ---

Flow Title=Flow
Program Version=6.10
Number of Profiles= 6
Profile Names=01pct,10pct,04pct,02pct,0_2pct,01plus
River Rch & RM=MLLSTNRN,Main            ,6328
     611     324     430     518     853     904
Boundary for River Rch & Prof#=MLLSTNRN,Main            , 1
Up Type= 0
Dn Type= 3
Dn Slope=0.03561
Boundary for River Rch & Prof#=MLLSTNRN,Main            , 2
Up Type= 0
Dn Type= 3
Dn Slope=0.03561
Boundary for River Rch & Prof#=MLLSTNRN,Main            , 3
Up Type= 0
Dn Type= 3
Dn Slope=0.03561
Boundary for River Rch & Prof#=MLLSTNRN,Main            , 4
Up Type= 0
Dn Type= 3
Dn Slope=0.03561
Boundary for River Rch & Prof#=MLLSTNRN,Main            , 5
Up Type= 0
Dn Type= 3
Dn Slope=0.03561
Boundary for River Rch & Prof#=MLLSTNRN,Main            , 6
Up Type= 0
Dn Type= 3
Dn Slope=0.03561
DSS Import GetInterval= 0
DSS Import GetPeak= 0
DSS Import FillOption= 0

--- MLLSTNRN.g01 (geometry) ---

Geom Title=Geometry
Program Version=6.10

River Reach=MLLSTNRN        ,Main
Reach XY= 30
2309735.97900003526579.3470000032309800.72300002526822.753999993
2309725.64899999526916.5190000092309748.61700003527320.042000011
     2309653.498527319.8270000072309667.65700002527402.804000005
2309426.94399999527615.604000002     2309360.273527644.849000007
2309327.50600001527562.2639999992309156.56646647 527835.57054733
2308748.69335278527935.6740731962308517.85462138528157.483797045
2308386.62900001528145.9774725042308294.63100003528245.024000019
2308073.42600001528181.9860000012308041.98600002528274.156000018
2307911.14400004528125.6079999952307799.12000002528250.695000023
2307700.18300003 528225.363000022307731.53399998528330.042000011
2307538.33399999528424.5729999992307456.10400002528545.662000015
     2307510.914528620.7810000182307387.16600002528639.033999994
     2307393.413528744.873000011      2307288.53528671.714000016
     2307096.035528872.3209999952306777.03900003529008.132000014
2306480.91900001529332.0160000032306270.88999324 529405.75391449

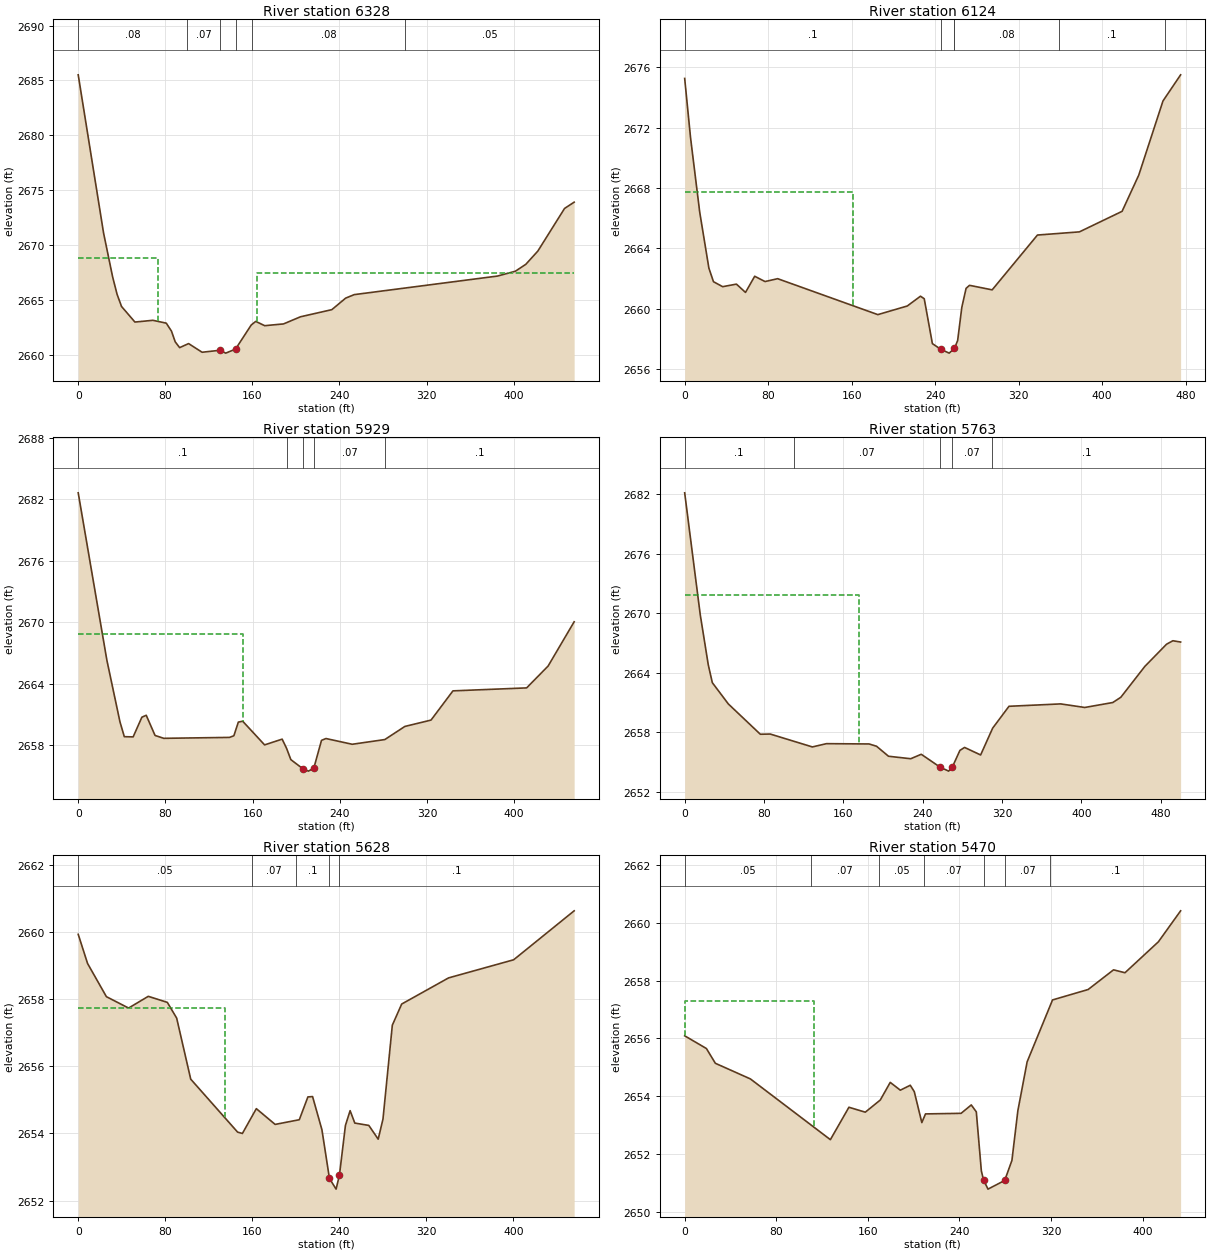
Type RM Length L Ch R = 1 ,6328    ,206.1,203.3,197.4
XS GIS Cut Line= 2
2309601.48138976526552.6829126992310044.72114306526658.134125036
#Sta/Elev= 30
       0 2685.51    23.3  2671.1    31.6 2667.11    35.7 2665.52    39.8 2664.41
    52.1 2662.99    68.6 2663.15    80.9 2662.89    85.7 2662.16    89.1 2661.19
    93.2 2660.66   101.4 2661.03   113.8 2660.24   130.2 2660.42   135.5 2660.16
  144.522660.526     159 2662.73   163.1 2663.05   171.3 2662.66   188.6 2662.82
   204.2 2663.47     233 2664.12   245.7 2665.17   253.6 2665.49   385.2 2667.18
   401.6 2667.62   411.2 2668.25   422.2 2669.45   446.8 2673.34   455.6 2673.91
#Mann= 6 ,-1,0
       0     .08       0     100     .07       0   130.2    .045       0
  144.52     .07       0     160     .08       0     300     .05       0
#XS Ineff= 2 , 0
           73.29  2668.8  164.16         2667.44
Permanent Ineff=
       F       F
Bank Sta=130.2,144.52
XS Rating Curve= 0 ,0
Exp/Cntr=0.3,0.1

Type RM Length L Ch R = 1 ,6124    ,190.9,195.1,197.9
XS GIS Cut Line= 4
2309555.04451442526701.3757827622309717.68738095526775.133054841
2309928.44063645 526751.289858452310010.76490215526770.916884083
#Sta/Elev= 30
       0 2675.25     5.6 2671.34    14.4  2666.4    23.2 2662.69    27.6 2661.79
    36.4 2661.46    49.6 2661.63    58.3 2661.08    67.1 2662.15      77  2661.8
    89.1 2661.99   185.1 2659.61   213.3 2660.18     226 2660.83   229.6 2660.66
   237.4 2657.69   245.5 2657.31   253.5 2657.06   258.5 2657.37   261.6 2657.89
   265.6 2660.09   269.7 2661.35     273 2661.55   294.7 2661.25   338.1 2664.88
   378.3 2665.09   419.2 2666.45   435.2 2668.85   458.4 2673.76   475.3 2675.49
#Mann= 6 ,-1,0
       0      .1       0   245.5    .045       0   258.5      .1       0
  258.59     .08       0  358.59      .1       0  460.68     .05       0
#XS Ineff= 2 , 0
          161.14 2667.72
Permanent Ineff=
       F       F
Bank Sta=245.5,258.5
XS Rating Curve= 0 ,0
Exp/Cntr(USF)=0,0
Exp/Cntr=0.3,0.1

Type RM Length L Ch R = 1 ,5929    ,167.4,166.7,168.9
XS GIS Cut Line= 2
2309514.04738963526891.4142328762309966.78440392526936.752703549
#Sta/Elev= 30
       0 2682.64    26.3 2666.31    38.3  2660.3    42.3 2658.85    50.4 2658.83
    58.4 2660.75    62.4 2660.94    70.5 2658.97    78.5 2658.69   138.8 2658.78
   142.8 2658.94   146.9 2660.27   150.9 2660.36     171 2658.05   187.1 2658.61
   191.1 2657.73   195.1 2656.61   205.9 2655.74   211.2 2655.49  216.16 2655.78
   223.2 2658.49   227.3 2658.67   251.4 2658.11   281.3 2658.57   299.7 2659.85
   323.7 2660.47   343.8 2663.32   411.4 2663.61   431.1 2665.74     455 2670.06
#Mann= 5 ,-1,0
       0      .1       0   191.1     .07       0   205.9    .045       0
  216.16     .07       0   281.3      .1       0
#XS Ineff= 2 , 0
          151.61 2668.83
Permanent Ineff=
       T       F
Bank Sta=205.9,216.16
XS Rating Curve= 0 ,0
Exp/Cntr(USF)=0,0
Exp/Cntr=0.3,0.1

Type RM Length L Ch R = 1 ,5763    ,132.4,134.9,136.9
XS GIS Cut Line= 2
2309488.57965745527039.3195934832309983.87734287527108.868693445
#Sta/Elev= 30
       0 2682.13    15.7 2669.84    23.8 2664.78    27.9 2662.98      44 2660.84
    76.3 2657.78    86.3  2657.8   128.8  2656.5     143 2656.83     186  2656.8
   193.5 2656.57   205.6 2655.56     228 2655.31   238.6 2655.76257.51232654.469
   266.2 2654.06   269.9 2654.46   277.6 2656.15   282.3 2656.45   298.5 2655.69
   310.6 2658.39   327.1  2660.6   379.3 2660.84   403.5 2660.48   431.8 2660.98
   439.9 2661.51   464.1 2664.62     486 2666.86   492.4 2667.21   500.2 2667.08
#Mann= 5 ,-1,0
       0      .1       0     110     .07       0257.5123    .045       0
   269.9     .07       0     310      .1       0
#XS Ineff= 2 , 0
           176.2 2671.85
Permanent Ineff=
       F       F
Bank Sta=257.5123,269.9
XS Rating Curve= 0 ,0
Exp/Cntr(USF)=0,0
Exp/Cntr=0.3,0.1

Type RM Length L Ch R = 1 ,5628    ,152.7,157.4,160.1
XS GIS Cut Line= 2
2309512.15728762527121.0517836362309935.37506649527290.339236434
#Sta/Elev= 30
       0 2659.94     8.6 2659.07    25.9 2658.08    46.3 2657.74    64.4 2658.09
    81.9 2657.91    90.5 2657.44   103.4 2655.62   146.5 2654.04   150.9    2654
   163.7 2654.74     181 2654.27   203.2 2654.41   211.1 2655.09   215.4  2655.1
     224 2654.11   230.9 2652.66     237 2652.34   240.1 2652.76   245.6 2654.24
   249.9 2654.68   254.2 2654.31   267.1 2654.24   275.7 2653.83   280.1 2654.43
   288.7 2657.23   297.3 2657.86   340.4 2658.64   400.2 2659.18   455.8 2660.64
#Mann= 5 ,-1,0
       0     .05       0     160     .07       0     200      .1       0
   230.9    .045       0   240.1      .1       0
#XS Ineff= 2 , 0
          134.46 2657.74
Permanent Ineff=
       F       F
Bank Sta=230.9,240.1
XS Rating Curve= 0 ,0
Exp/Cntr(USF)=0,0
Exp/Cntr=0.3,0.1

Type RM Length L Ch R = 1 ,5470    ,313.8,324.3,327.8
XS GIS Cut Line= 3
 2309503.5801077527208.7779664412309686.27094688527288.666323544
2309896.99329237527390.291773191
#Sta/Elev= 30
       0 2656.09      19 2655.65    26.8 2655.14    57.4  2654.6   127.3  2652.5
   143.5 2653.62   157.8 2653.45   170.9 2653.87   179.6 2654.48   188.4 2654.21
   197.1 2654.38   200.6 2654.16   207.2 2653.09   210.4 2653.39   241.5 2653.41
   250.4  2653.7   254.8 2653.46   259.2 2651.42   261.1 2651.11     265 2650.79
   279.6 2651.09   285.9 2651.78   291.1  2653.5   299.2 2655.19   321.4 2657.33
   352.5 2657.69   374.7 2658.37   384.7 2658.27   413.9 2659.34   433.3 2660.41
#Mann= 7 ,-1,0
       0     .05       0     110     .07       0     170     .05       0
  209.39     .07       0   261.1    .045       0   279.6     .07       0
  319.39      .1       0
#XS Ineff= 2 , 0
          112.72 2657.29
Permanent Ineff=
       F       F
Bank Sta=261.1,279.6
XS Rating Curve= 0 ,0
Exp/Cntr(USF)=0,0
Exp/Cntr=0.3,0.1

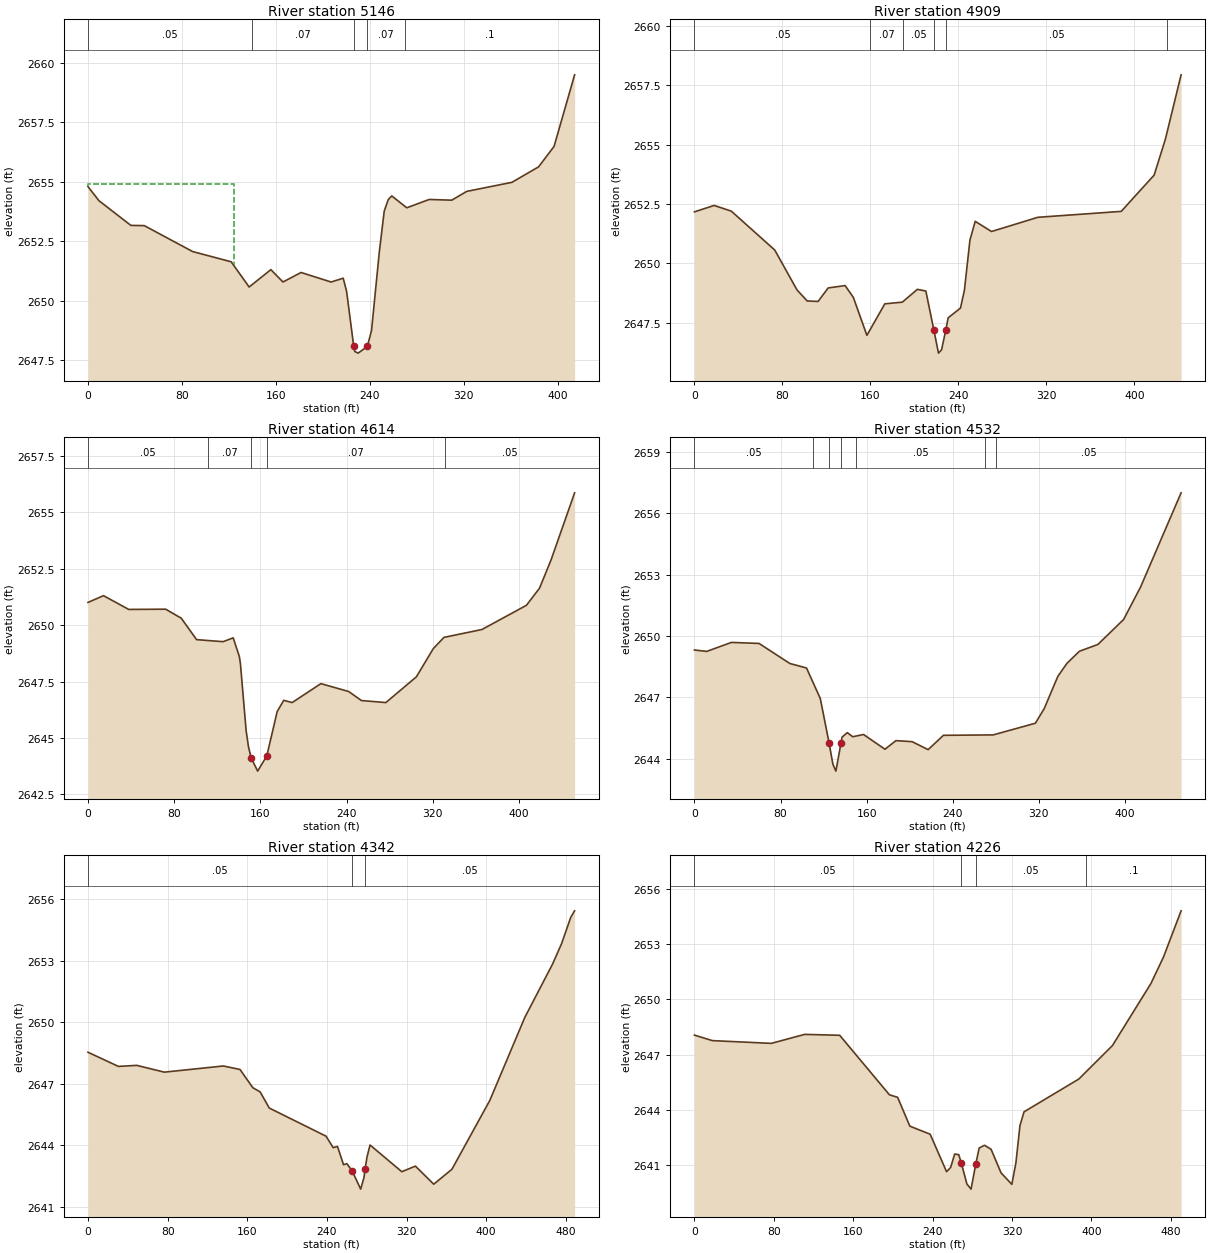
Type RM Length L Ch R = 1 ,5146    ,236.6,237.6,237.9
XS GIS Cut Line= 2
2309466.33579719 527267.717318772309725.61305045527590.829729922
#Sta/Elev= 30
       0 2654.79     9.3  2654.2    36.5 2653.16    47.9 2653.15    89.1 2652.06
   121.9 2651.63   137.2 2650.57   155.7  2651.3     166 2650.78   181.4 2651.18
     207 2650.78   217.3 2650.94   220.2 2650.38  226.17  2648.1   227.1 2647.86
     230 2647.79   237.8 2648.07   241.4 2648.74     248 2652.03   252.2 2653.76
   255.6 2654.24   258.6  2654.4   271.4  2653.9   290.5 2654.25   309.7 2654.22
   322.5 2654.59   360.9 2654.97   383.6 2655.62   396.8 2656.48   414.3 2659.49
#Mann= 5 ,-1,0
       0     .05       0     140     .07       0  226.17    .045       0
   237.8     .07       0     270      .1       0
#XS Ineff= 2 , 0
          123.99 2654.89
Permanent Ineff=
       F       F
Bank Sta=226.17,237.8
XS Rating Curve= 0 ,0
Exp/Cntr(USF)=0,0
Exp/Cntr=0.3,0.1

Type RM Length L Ch R = 1 ,4909    ,288.7,294.3,283.3
XS GIS Cut Line= 2
2309305.73194805527421.9565971542309564.28543768527781.105369256
#Sta/Elev= 30
       0 2652.17    17.9 2652.44    33.5  2652.2      73 2650.56    93.2 2648.88
   102.5 2648.41   112.4 2648.39   121.6 2648.96     137 2649.06   144.5 2648.56
   156.8 2646.96   173.1 2648.29     189 2648.36   202.7  2648.9   210.4 2648.83
  217.752647.171   221.9 2646.21   224.7 2646.35  228.622647.199   230.7  2647.7
   241.9 2648.11   245.5 2648.87   250.5 2650.98   255.3 2651.77   270.1 2651.34
   312.3 2651.94   388.1 2652.19     418 2653.72   428.2 2655.23   442.5 2657.95
#Mann= 6 ,-1,0
       0     .05       0     160     .07       0     190     .05       0
  217.75    .045       0  228.62     .05       0     430      .1       0
Bank Sta=217.75,228.62
XS Rating Curve= 0 ,0
Exp/Cntr(USF)=0,0
Exp/Cntr=0.3,0.1

Type RM Length L Ch R = 1 ,4614    ,82.2,82.5,84
XS GIS Cut Line= 3
2309193.33633694527488.3106326312309224.33472034527540.994326352
2309483.05274414527833.599878987
#Sta/Elev= 30
       0 2651.01    14.4 2651.31    37.8  2650.7    72.1 2650.71    86.6 2650.31
   100.8 2649.36   125.4 2649.27   134.8 2649.44   140.5 2648.61   141.5 2648.29
   146.8 2645.32     149  2644.6   151.5 2644.11   157.5 2643.53     166 2644.21
   175.6 2646.17   181.7 2646.67   189.5 2646.57   216.2 2647.41     242 2647.06
   253.8 2646.66   276.5 2646.57   304.8 2647.71   320.5 2648.96   330.4 2649.46
   365.7 2649.81   406.9 2650.88   419.1 2651.64   429.8 2652.89   451.7 2655.87
#Mann= 5 ,-1,0
       0     .05       0  111.13     .07       0   151.5    .045       0
     166     .07       0  331.13     .05       0
Bank Sta=151.5,166
XS Rating Curve= 0 ,0
Exp/Cntr(USF)=0,0
Exp/Cntr=0.3,0.1

Type RM Length L Ch R = 1 ,4532    ,186.6,190.1,191.5
XS GIS Cut Line= 4
2309141.29881008527551.9544359032309332.52502598527804.454727518
2309372.42885265527818.684183517 2309441.4912161527880.975727026
#Sta/Elev= 30
       0 2649.32    11.4 2649.25    34.3 2649.69      60 2649.64    88.6 2648.66
   104.1 2648.44   116.9 2646.95  125.03 2644.79   128.6 2643.74   131.4  2643.4
   136.2 2644.79   137.1 2645.06     142 2645.28     147 2645.08   157.1 2645.19
     177 2644.47   187.2 2644.89   202.2 2644.84   217.1 2644.45   231.3 2645.15
   277.5 2645.17   316.7 2645.74   324.9 2646.45   337.6 2648.03   346.1 2648.67
   357.7 2649.26   374.8 2649.59   398.7 2650.81   414.5  2652.4   452.1    2657
#Mann= 7 ,-1,0
       0     .05       0     110     .07       0  125.03    .045       0
   136.2     .07       0     150     .05       0     270     .07       0
     280     .05       0
Bank Sta=125.03,136.2
XS Rating Curve= 0 ,0
Exp/Cntr(USF)=0,0
Exp/Cntr=0.3,0.1

Type RM Length L Ch R = 1 ,4342    ,105.1,115.9,123.1
XS GIS Cut Line= 2
2309025.38220118527594.4425430482309264.87253744528020.572495855
#Sta/Elev= 30
       0 2648.54    30.5 2647.85      49  2647.9    76.6 2647.57     136 2647.87
   152.7  2647.7   165.6 2646.81   172.9 2646.61   182.1 2645.82   239.1 2644.45
   246.3 2643.89   250.6 2643.95   256.7 2643.06   260.1 2643.11   265.5 2642.74
   273.9 2641.87   277.2 2642.43   278.4 2642.86   280.2 2643.42   283.3 2644.02
   315.2 2642.72   328.9 2642.99   347.3 2642.11   365.6 2642.84   403.6 2646.19
   438.8 2650.24   466.6 2652.83   475.7 2653.83   484.9 2655.11   488.8 2655.43
#Mann= 3 ,-1,0
       0     .05       0   265.5    .045       0   278.4     .05       0
Bank Sta=265.5,278.4
XS Rating Curve= 0 ,0
Exp/Cntr(USF)=0,0
Exp/Cntr=0.3,0.1

Type RM Length L Ch R = 1 ,4226    ,134.5,130.6,123
XS GIS Cut Line= 4
2309008.87848254527605.4055413022309084.81668507527742.135545941
2309041.26640067527925.6439439192309092.99156243528061.664545546
#Sta/Elev= 30
       0 2648.06      18 2647.76    77.5 2647.61   111.1  2648.1   146.4 2648.05
   196.5 2644.81   204.8 2644.67   217.1  2643.1   237.6 2642.66   254.1 2640.62
   258.2 2640.85   262.3 2641.58   266.4 2641.55   269.1 2641.07   274.6 2639.95
   278.8 2639.67   283.6 2641.05     287 2641.91   292.4 2642.06     299 2641.84
     309 2640.56   319.9 2639.93     324  2641.1   328.1 2643.13   332.2 2643.88
   387.5 2645.67   421.3 2647.49   460.1 2650.87   472.9 2652.33   490.5 2654.83
#Mann= 4 ,-1,0
       0     .05       0   269.1    .045       0   283.6     .05       0
  395.01      .1       0
Bank Sta=269.1,283.6
XS Rating Curve= 0 ,0
Exp/Cntr(USF)=0,0
Exp/Cntr=0.3,0.1

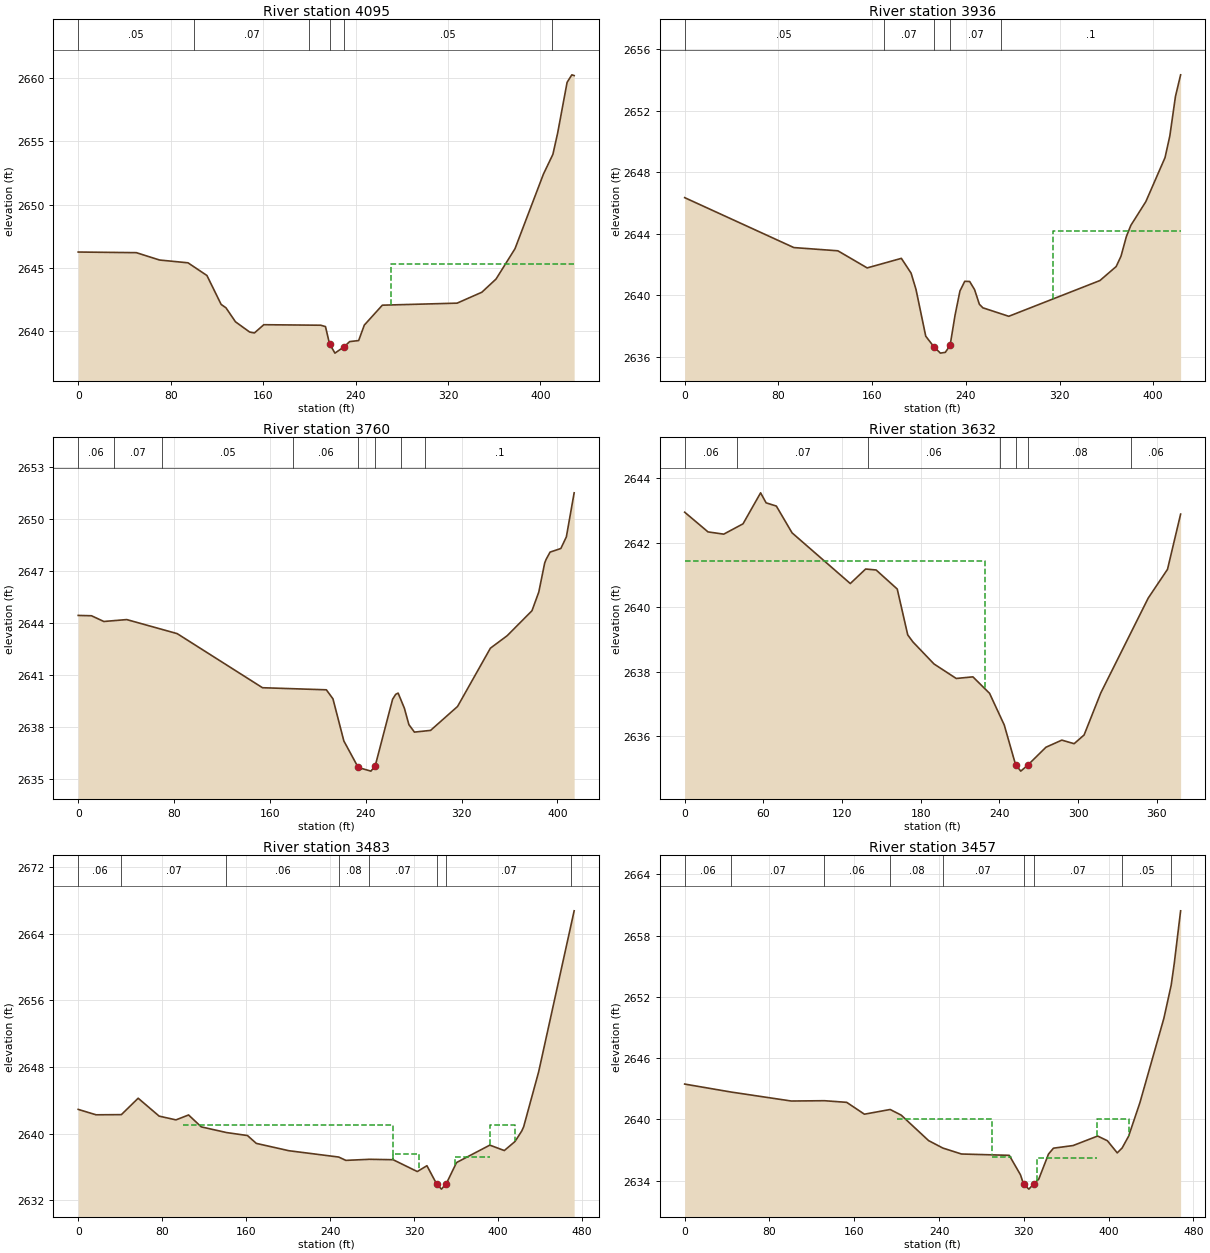
Type RM Length L Ch R = 1 ,4095    ,156,159,154.8
XS GIS Cut Line= 2
2308896.77442328527672.4769351792308991.44066057 528091.09837451
#Sta/Elev= 30
       0 2646.26    50.3 2646.21    70.4 2645.63      95 2645.41   111.4 2644.41
   123.7 2642.13   127.9 2641.86   136.1 2640.76   148.4 2639.95   152.5 2639.88
   160.6 2640.53   209.9 2640.49     214 2640.38   217.5 2639.02   222.2 2638.29
   230.4 2638.81   234.9  2639.2   242.7 2639.28   247.6  2640.5   263.2 2642.07
   327.9 2642.23   349.3 2643.09   361.6 2644.13     378 2646.52   402.6  2652.4
   410.8 2653.96   414.9 2655.63   423.1 2659.64   427.2 2660.23   429.2 2660.17
#Mann= 6 ,-1,0
       0     .05       0     100     .07       0     200     .05       0
   217.5    .045       0   230.4     .05       0     410      .1       0
#XS Ineff= 2 , 0
                          270.53          2645.3
Permanent Ineff=
       F       F
Bank Sta=217.5,230.4
XS Rating Curve= 0 ,0
Exp/Cntr(USF)=0,0
Exp/Cntr=0.3,0.1

Type RM Length L Ch R = 1 ,3936    ,177.4,176.2,172.5
XS GIS Cut Line= 2
 2308757.6384015527711.7052283612308876.80483256528117.954425157
#Sta/Elev= 30
       0 2646.35    93.2 2643.11   130.8  2642.9   155.8 2641.79     185 2642.41
   193.3 2641.45   197.5 2640.39   205.8 2637.36   212.7 2636.68   218.3 2636.26
   222.5 2636.31   226.6 2636.76   230.8 2638.71     235 2640.29   239.1 2640.92
   243.3 2640.91   247.5 2640.38   251.6 2639.43   254.6  2639.2   276.7 2638.65
   354.5 2640.97   368.4 2641.88   372.5 2642.55   377.1 2643.83   380.9 2644.55
   393.7 2646.09   410.1 2648.95   414.2 2650.36     419 2652.92   423.4 2654.32
#Mann= 5 ,-1,0
       0     .05       0     170     .07       0   212.7    .045       0
   226.6     .07       0     270      .1       0
#XS Ineff= 2 , 0
                          314.81         2644.18
Permanent Ineff=
       F       F
Bank Sta=212.7,226.6
XS Rating Curve= 0 ,0
Exp/Cntr(USF)=0,0
Exp/Cntr=0.3,0.1

Type RM Length L Ch R = 1 ,3760    ,126.4,128.1,129.7
XS GIS Cut Line= 3
2308603.75524652527802.6647549652308634.34134097527896.828285641
2308781.99663022528174.906079183
#Sta/Elev= 30
       0 2644.43    11.1 2644.41    21.4 2644.08    40.5 2644.19    82.6 2643.38
   153.8 2640.26   207.1 2640.14   212.6 2639.62   221.7 2637.19   233.7 2635.66
   244.3 2635.45   247.9 2635.76   262.4  2639.6     265 2639.88     267 2639.95
   272.2 2639.08     276 2638.13   280.6  2637.7   294.1  2637.8   316.6 2639.18
     344 2642.54     358 2643.26   378.7  2644.7   384.4 2645.78   389.3 2647.45
   390.5 2647.66   393.8 2648.08   402.8 2648.29   407.4 2648.96   413.9  2651.5
#Mann= 8 ,-1,0
       0     .06       0      30     .07       0      70     .05       0
  179.01     .06       0   233.7    .045       0   247.9     .06       0
  269.01     .07       0  289.01      .1       0
Bank Sta=233.7,247.9
XS Rating Curve= 0 ,0
Exp/Cntr(USF)=0,0
Exp/Cntr=0.3,0.1

Type RM Length L Ch R = 1 ,3632    ,140.2,148.8,156.5
XS GIS Cut Line= 3
2308556.10644424527831.4201540672308567.89374598 528021.53160854
2308630.35297562528198.603080324
#Sta/Elev= 30
       0 2642.94    17.8 2642.33    29.8 2642.26    44.5 2642.58    57.9 2643.54
    62.1 2643.23    69.9 2643.13    81.9  2642.3   126.3 2640.73     138 2641.18
     146 2641.15   162.1 2640.56   170.1 2639.14   174.1 2638.92   190.1 2638.24
   207.1 2637.79   219.8 2637.84   232.5 2637.33   243.7 2636.35  252.34 2635.12
   256.3 2634.92   261.5  2635.1   275.5 2635.66   287.6 2635.88     297 2635.77
   304.6 2636.04   317.3 2637.34   353.5 2640.28   368.2 2641.17   378.2 2642.88
#Mann= 7 ,-1,0
       0     .06       0      40     .07       0     140     .06       0
  240.48     .08       0  252.34    .045       0   261.5     .08       0
  340.48     .06       0
#XS Ineff= 2 , 0
          228.66 2641.44
Permanent Ineff=
       F       F
Bank Sta=252.34,261.5
XS Rating Curve= 0 ,0
Exp/Cntr(USF)=0,0
Exp/Cntr=0.5,0.3

Type RM Length L Ch R = 1 ,3483    ,25.3,25.7,25.5
XS GIS Cut Line= 5
2308549.70948188527832.219774361 2308559.3135965527998.420651802
2308500.17481717528114.3064931442308429.82181684528237.542285666
2308445.23935145 528267.65062253
#Sta/Elev= 30
       0 2642.92      17 2642.27    41.1 2642.29    57.1 2644.26    77.1 2642.11
    93.1 2641.66   105.1 2642.25   117.2 2640.82   141.2 2640.14   161.2 2639.78
   169.6 2638.84   200.6 2637.96   248.1  2637.2   254.9  2636.8   277.4 2636.93
   299.9 2636.88   322.9 2635.46   332.1 2636.16   341.3 2633.98   345.9 2633.35
   350.6 2634.02   360.3 2636.54     392 2638.63   405.8 2637.98     416 2639.07
   422.4 2640.33   424.2 2640.83   438.5 2647.43   469.1 2664.92   472.3 2666.75
#Mann= 8 ,-1,0
       0     .06       0    41.1     .07       0   141.2     .06       0
   248.1     .08       0   277.4     .07       0   341.3    .045       0
   350.6     .07       0   469.1      .1       0
#XS Ineff= 4 ,-1
     100     300    2641     300     325  2637.6     359     392  2637.2
     392     416    2641
Permanent Ineff=
       F       F       F       F
Bank Sta=341.3,350.6
XS Rating Curve= 0 ,0
Exp/Cntr(USF)=0,0
Exp/Cntr=0.5,0.3

Type RM Length L Ch R = 1 ,3457    ,71.5,64.7,61.4
XS GIS Cut Line= 5
2308520.73887666527837.4156609632308527.17127129527990.343824187
2308475.14992443 528107.696144122308405.89625582528226.434799687
2308419.03713423528273.783056348
#Sta/Elev= 30
       0 2643.46    43.8 2642.68   100.6  2641.8   131.9 2641.83   152.9 2641.67
   169.6 2640.51   193.9 2640.97   204.3 2640.42   230.2 2637.92   243.7 2637.19
   261.2 2636.61   306.3 2636.48   316.9 2634.57   319.8 2633.65   324.8 2633.17
   329.5 2633.69   334.1 2634.14   343.3  2636.6     348 2637.18   366.6 2637.44
   389.7 2638.37   398.9 2637.91   408.2 2636.72   412.8  2637.2   418.9 2638.35
   429.5 2641.61   452.2  2649.9   459.1 2653.15     462 2655.28     468 2660.43
#Mann= 9 ,-1,0
       0     .06       0    43.8     .07       0   131.9     .06       0
   193.9     .08       0   243.7     .07       0   319.8    .045       0
   329.5     .07       0   412.8     .05       0   459.1      .1       0
#XS Ineff= 4 ,-1
     200     290    2640     290     308 2636.36     332   389.3  2636.2
   389.3     419    2640
Permanent Ineff=
       F       F       F       F
Bank Sta=319.8,329.5
XS Rating Curve= 0 ,0
Exp/Cntr(USF)=0,0
Exp/Cntr=0.5,0.3

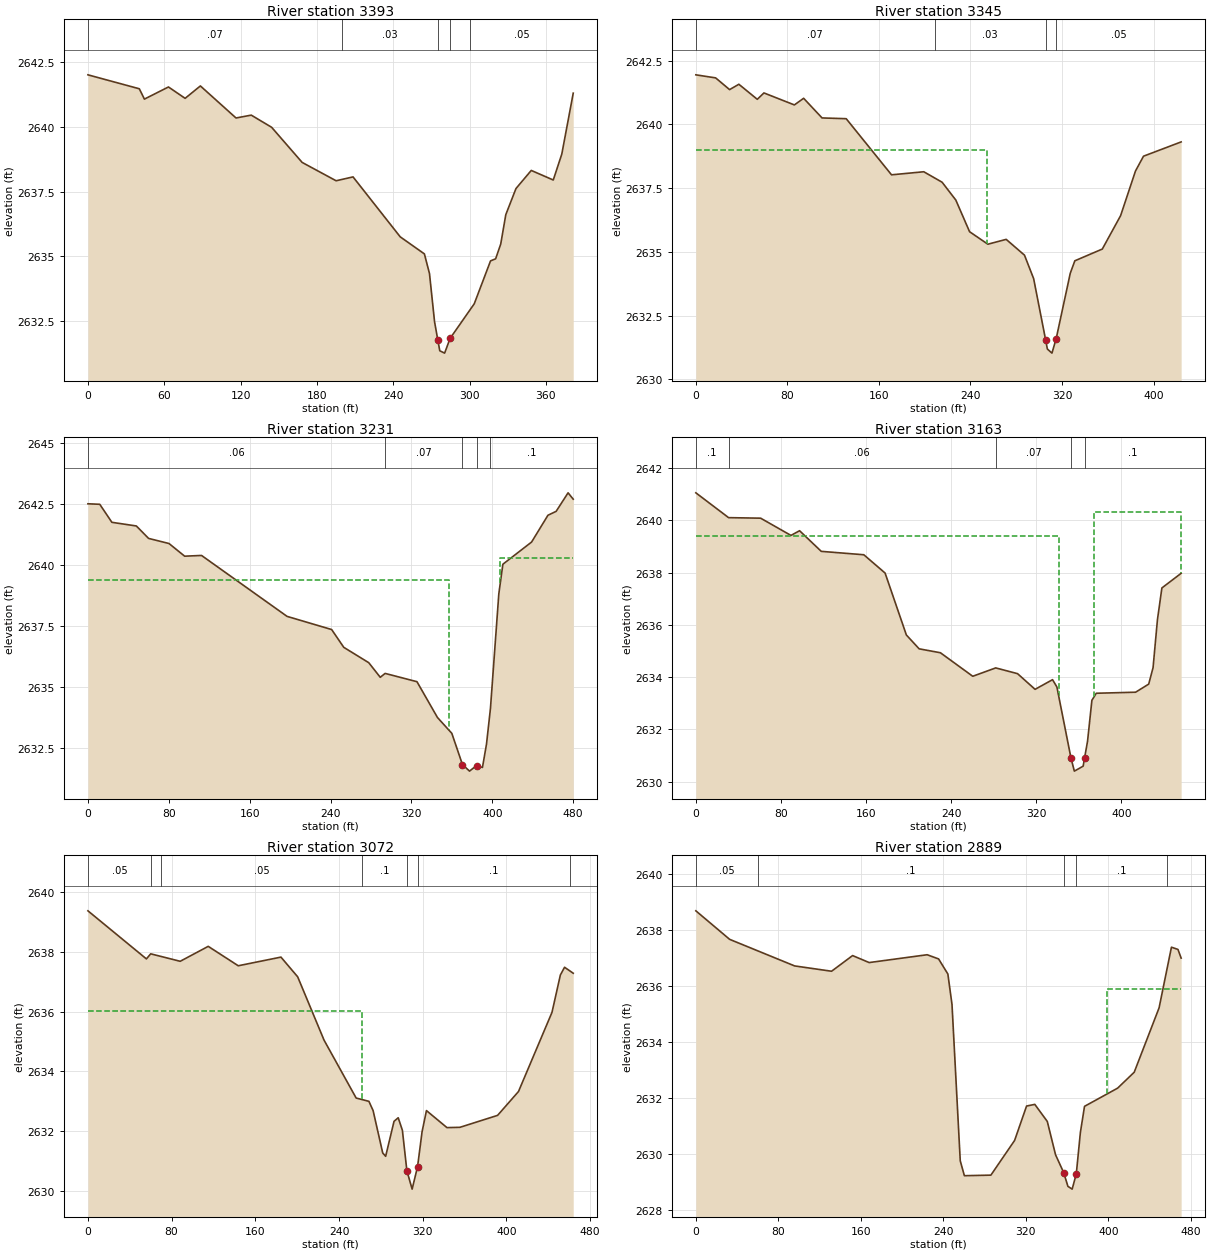
Type RM Length L Ch R = 1 ,3393    ,47.7,47.5,47.8
XS GIS Cut Line= 2
2308379.24228142527864.8374817472308391.44420109528246.136064471
#Sta/Elev= 30
       0 2642.02    40.4 2641.48    44.4 2641.08    63.3 2641.55    76.4 2641.11
    88.4 2641.59   116.4 2640.35   128.4 2640.46   144.4 2639.99   168.4 2638.63
   195.1 2637.92   208.4 2638.07   245.5 2635.75   264.5 2635.09   268.5 2634.33
   272.5 2632.46  275.092631.744   276.6 2631.34   280.4 2631.25   284.7 2631.82
   303.7 2633.16   316.5 2634.82   320.5  2634.9   324.5 2635.47   328.5 2636.61
   336.5 2637.62   348.5 2638.32   365.8 2637.95   372.5 2638.95   381.5 2641.31
#Mann= 5 ,-1,0
       0     .07       0     200     .03       0  275.09    .045       0
   284.7     .03       0     300     .05       0
Bank Sta=275.09,284.7
XS Rating Curve= 0 ,0
Exp/Cntr(USF)=0,0
Exp/Cntr=0.3,0.1

Type RM Length L Ch R = 1 ,3345    ,111.1,114.6,118.3
XS GIS Cut Line= 3
2308321.80538873527860.0158725292308349.34786552528046.593941143
2308346.68246454528282.037694394
#Sta/Elev= 30
       0 2641.94    17.3 2641.82    29.5 2641.36    37.6 2641.57    53.7 2640.98
    59.5 2641.23    86.1 2640.76    94.2 2641.02   110.3 2640.25   131.4 2640.22
     171 2638.02   199.2 2638.14   215.2 2637.73   227.2 2637.03   239.2 2635.79
   255.2  2635.3   271.2 2635.49   287.2 2634.87   295.2 2633.95  305.612631.563
   307.2 2631.19   311.2 2631.03   314.9  2631.6   327.2 2634.16   331.2 2634.65
   355.2 2635.11   371.2 2636.42   384.2 2638.17   391.2 2638.75   424.1 2639.31
#Mann= 4 ,-1,0
       0     .07       0   208.6     .03       0  305.61    .045       0
   314.9     .05       0
#XS Ineff= 2 , 0
          254.43 2638.99
Permanent Ineff=
       F       F
Bank Sta=305.61,314.9
XS Rating Curve= 0 ,0
Exp/Cntr(USF)=0,0
Exp/Cntr=0.5,0.3

Type RM Length L Ch R = 1 ,3231    ,66.9,67.7,68.6
XS GIS Cut Line= 4
2308283.81434509527873.6124643972308305.09964486528045.864181536
2308294.42220585528179.1334525222308267.71523961528349.894159136
#Sta/Elev= 30
       0 2642.51    11.7 2642.49    23.7 2641.75    47.9  2641.6      60 2641.09
    80.2 2640.88    95.7 2640.36   112.4 2640.39     197 2637.89   241.1 2637.35
   253.1 2636.62   277.8 2635.99   289.2 2635.39     294 2635.55   325.5 2635.21
   345.8 2633.74     360 2633.09   370.5 2631.81   377.5 2631.54   384.5 2631.77
   390.3 2631.69   394.3 2632.65   398.2 2634.11   406.5 2638.82   410.5 2640.03
   438.9 2640.94   455.1 2642.04   463.2  2642.2     475 2642.96   480.1  2642.7
#Mann= 5 ,-1,0
       0     .06       0     294     .07       0   370.5    .045       0
   384.5     .07       0   398.2      .1       0
#XS Ineff= 2 , 0
             357  2639.4     408          2640.3
Permanent Ineff=
       F       F
Bank Sta=370.5,384.5
XS Rating Curve= 0 ,0
Exp/Cntr(USF)=0,0
Exp/Cntr=0.5,0.3

Type RM Length L Ch R = 1 ,3163    ,89.1,91.2,94.4
XS GIS Cut Line= 4
2308212.11708513527885.3027193842308234.16381541528003.817886526
2308233.72024864528166.8932722362308193.98853353528334.847892588
#Sta/Elev= 30
       0 2641.05    30.8  2640.1    60.9 2640.08    89.4 2639.42    97.5  2639.6
   117.9 2638.81   157.9 2638.68   177.9 2637.98   197.9 2635.61   209.9 2635.08
   229.9 2634.93   260.3 2634.03   281.9 2634.35   302.4 2634.13   318.9 2633.53
   335.3  2633.9   339.4 2633.62  352.65  2630.9   355.8  2630.4   364.1 2630.59
   365.4  2630.9   368.2 2631.54   372.3 2633.11   376.4 2633.38   413.4 2633.42
   425.7 2633.73   429.8 2634.36   433.9 2636.19   438.1 2637.41   456.2 2637.97
#Mann= 5 ,-1,0
       0      .1       0    30.8     .06       0   281.9     .07       0
  352.65    .045       0   365.4      .1       0
#XS Ineff= 2 , 0
             341  2639.4     374          2640.3
Permanent Ineff=
       F       F
Bank Sta=352.65,365.4
XS Rating Curve= 0 ,0
Exp/Cntr(USF)=0,0
Exp/Cntr=0.5,0.3

Type RM Length L Ch R = 1 ,3072    ,183.4,183.1,174
XS GIS Cut Line= 5
2308111.59347461527909.6507796982308126.46783477528031.072572984
2308134.27801996528210.1480831582308124.01187149528226.351198413
2308127.80790619528369.395318291
#Sta/Elev= 30
       0 2639.38    55.9 2637.77      60 2637.94    88.2 2637.69     115 2638.19
   143.7 2637.54   184.5 2637.83   200.5 2637.17   225.7 2635.05   256.4 2633.11
   268.6    2633   272.6 2632.69   281.8 2631.27   284.6 2631.16   292.6 2632.33
   296.6 2632.45   300.6 2632.03 304.8632630.682   309.9 2630.06315.07562630.808
   319.4 2631.98   323.6 2632.69   343.2 2632.12   355.6 2632.13   391.6 2632.53
   411.6 2633.33   443.6 2635.98   451.6 2637.23   455.6 2637.49   463.9 2637.29
#Mann= 7 ,-1,0
       0     .05       0      60      .1       0      70     .05       0
  262.33      .1       0 304.863    .045       0315.0756      .1       0
  460.76     .07       0
#XS Ineff= 2 , 0
          261.67 2636.01
Permanent Ineff=
       F       F
Bank Sta=304.863,315.0756
XS Rating Curve= 0 ,0
Exp/Cntr(USF)=0,0
Exp/Cntr=0.3,0.1

Type RM Length L Ch R = 1 ,2889    ,113.5,123,126.6
XS GIS Cut Line= 3
2307998.03563931527913.6335344462308022.89528703527986.039572541
2308058.23896715528378.476296649
#Sta/Elev= 30
       0 2638.69    32.8 2637.67    95.8 2636.72   131.6 2636.53     152 2637.09
   168.1 2636.84   224.3 2637.12   235.4 2636.97   244.4 2636.43   248.4 2635.34
   256.4 2629.75   260.4 2629.22   286.1 2629.24   309.1 2630.48   320.7 2631.71
   328.7 2631.77   340.8 2631.16   348.8 2629.97   356.7 2629.33   360.8 2628.84
   364.9 2628.74   368.9 2629.28   372.9 2630.77   376.9  2631.7     409 2632.35
   425.1 2632.92   449.2 2635.22   461.2 2637.39   467.5 2637.31   470.6    2637
#Mann= 5 ,-1,0
       0     .05       0      60      .1       0   356.7    .045       0
   368.9      .1       0  456.55     .06       0
#XS Ineff= 2 , 0
                          398.55          2635.9
Permanent Ineff=
       F       F
Bank Sta=356.7,368.9
XS Rating Curve= 0 ,0
Exp/Cntr(USF)=0,0
Exp/Cntr=0.3,0.1