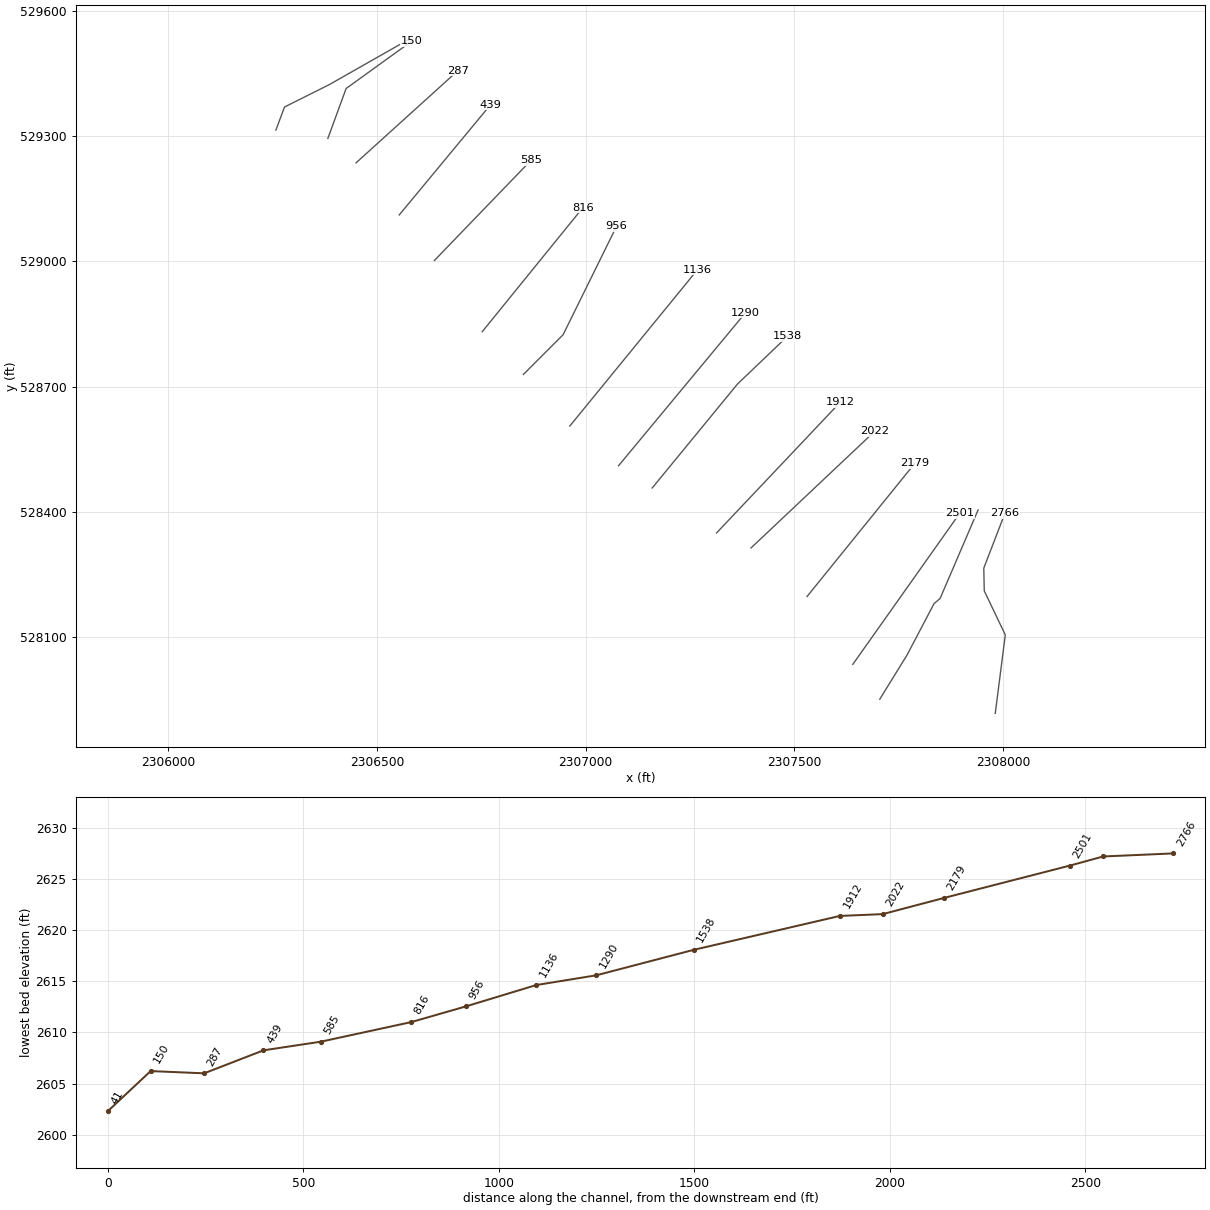
HEC-RAS study MLLSTNRN.prj: MLLSTNRN

--- MLLSTNRN.g01 (geometry) --- (continued)

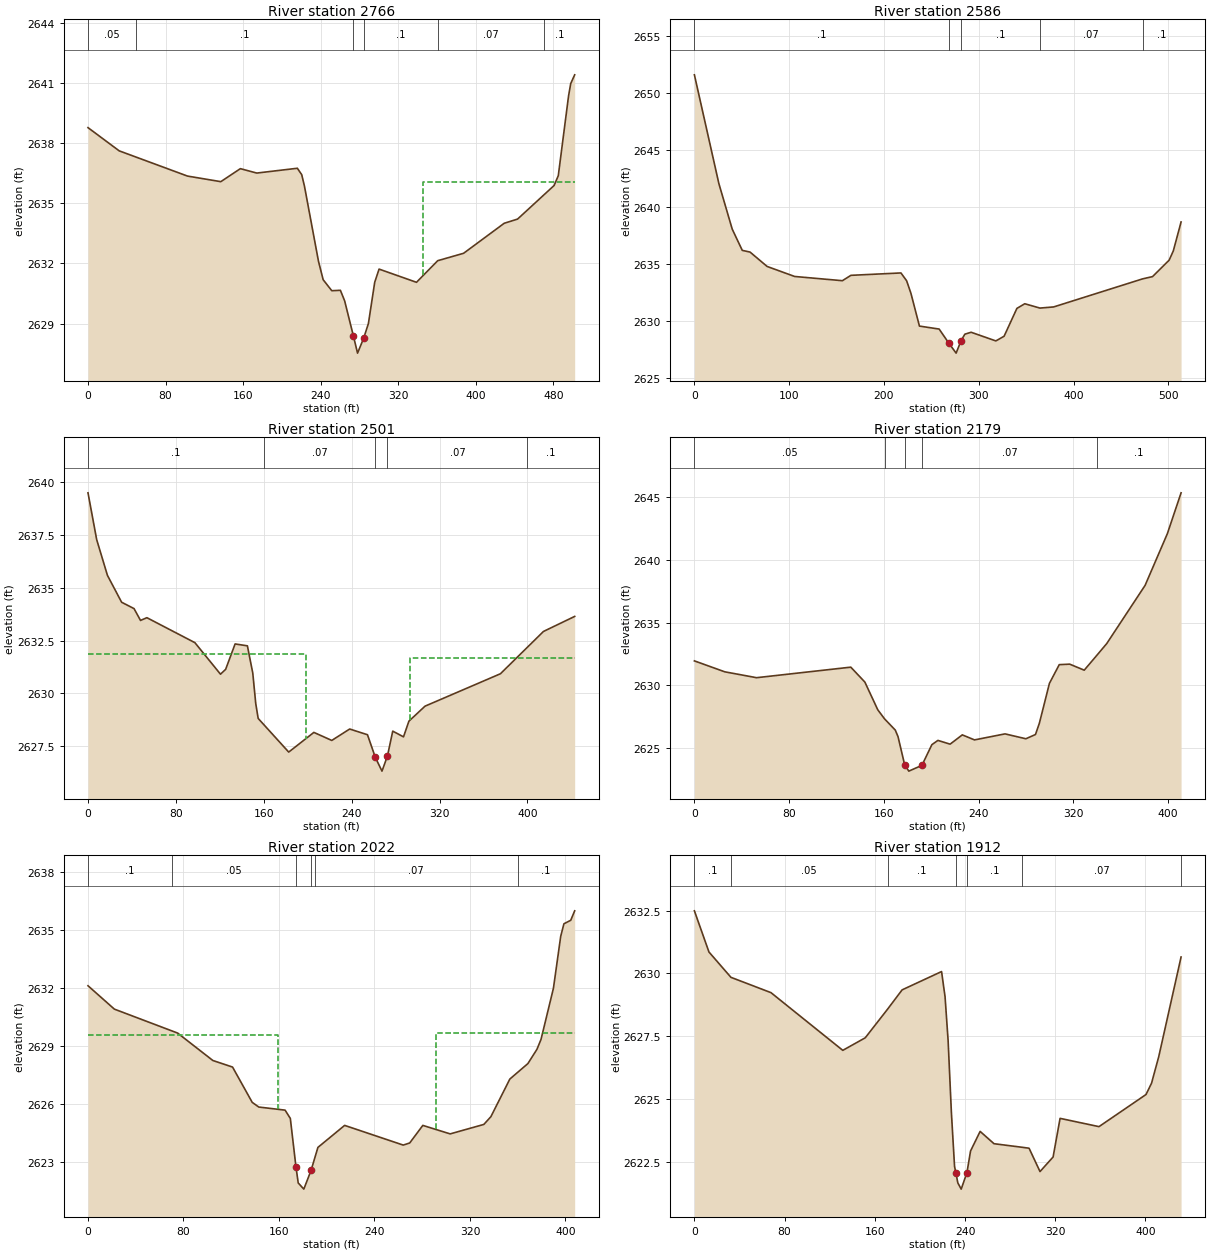
Type RM Length L Ch R = 1 ,2766    ,191.7,179.6,164.4
XS GIS Cut Line= 5
2307981.25680721527917.2737024152308005.30356797528105.314273239
2307954.94815546528210.6984969752307953.75048233528265.160671359
2308004.53882999528397.019325043
#Sta/Elev= 30
       0 2638.79    32.2 2637.63   102.6 2636.37     137 2636.09   157.2 2636.74
   174.1 2636.52     216 2636.76   220.5 2636.44   223.3 2635.87   237.8 2632.11
   242.6 2631.19   251.5 2630.64   260.4 2630.66   264.8 2630.13   273.7  2628.4
   278.1 2627.52   284.42628.265   289.3    2629   295.8 2631.06   300.3 2631.72
   338.9 2631.06   360.8 2632.14   387.5 2632.51   429.4 2634.01   443.2 2634.22
   480.9  2635.9   485.2 2636.39   495.8 2640.38     498 2640.99   502.1 2641.43
#Mann= 6 ,-1,0
       0     .05       0      50      .1       0   273.7    .045       0
   284.4      .1       0  360.84     .07       0  470.84      .1       0
#XS Ineff= 2 , 0
                          345.89         2636.06
Permanent Ineff=
       F       F
Bank Sta=273.7,284.4
XS Rating Curve= 0 ,0
Exp/Cntr(USF)=0,0
Exp/Cntr=0.3,0.1

Type RM Length L Ch R = 1 ,2586    ,82.4,85,84.7
XS GIS Cut Line= 5
2307704.58859149527951.2512343942307769.66371517528056.698717332
2307834.76417439528180.4959494222307849.06265759528192.500878328
2307940.16297949528404.682033248
#Sta/Elev= 30
       0 2651.62    25.8 2642.09    39.9 2638.09    50.5 2636.23    58.7 2636.08
    76.7 2634.82   105.8 2633.94   156.1 2633.57   165.1 2634.04   217.9 2634.25
   223.9 2633.56   228.4 2632.47   237.4 2629.59   258.2 2629.33   268.1 2628.13
   276.1 2627.22   281.3 2628.31   285.3 2628.88   291.9 2629.05     318 2628.29
   326.7  2628.7   340.2 2631.14   348.5 2631.55   364.5 2631.17     379 2631.27
   472.8 2633.73   483.3 2633.93   500.8 2635.37   505.2 2636.18   513.4 2638.72
#Mann= 5 ,-1,0
       0      .1       0   268.1    .045       0   281.3      .1       0
   364.5     .07       0   472.8      .1       0
Bank Sta=268.1,281.3
XS Rating Curve= 0 ,0
Exp/Cntr(USF)=0,0
Exp/Cntr=0.3,0.1

Type RM Length L Ch R = 1 ,2501    ,318.8,322.3,318.8
XS GIS Cut Line= 2
2307639.96058881528034.746086809 2307895.8975828528396.307871962
#Sta/Elev= 30
       0 2639.48     7.9 2637.27    17.7 2635.58    30.6 2634.31    41.9 2634.01
    47.8 2633.45    53.6 2633.58    97.3  2632.4   120.6 2630.91   125.3 2631.14
   133.9 2632.34   145.1 2632.25     150 2630.96   152.7 2629.52   154.9 2628.82
   182.7 2627.23   205.6 2628.16   221.9 2627.78   238.2 2628.32   254.4 2628.05
  261.562626.977   267.6 2626.33   272.5 2627.03   277.4 2628.22   287.2 2627.95
   292.1 2628.69   306.8  2629.4   375.4 2630.93   414.6 2632.93     443 2633.64
#Mann= 5 ,-1,0
       0      .1       0     160     .07       0  261.56    .045       0
   272.5     .07       0     400      .1       0
#XS Ineff= 2 , 0
          198.07 2631.88  293.08         2631.69
Permanent Ineff=
       F       F
Bank Sta=261.56,272.5
XS Rating Curve= 0 ,0
Exp/Cntr(USF)=0,0
Exp/Cntr=0.3,0.1

Type RM Length L Ch R = 1 ,2179    ,157.5,156.4,155.6
XS GIS Cut Line= 2
2307530.27330568 528197.245765532307788.91862764528516.828467013
#Sta/Elev= 30
       0 2631.95    25.6 2631.08    52.5 2630.61   132.1 2631.45     144 2630.26
   154.9 2628.05   160.6 2627.33   169.7 2626.43     172 2625.91   177.6 2623.67
   181.1 2623.16  192.19 2623.62   200.6 2625.27   205.7 2625.61     216 2625.31
   226.3 2626.05   236.6 2625.65   262.4 2626.13     280 2625.74   288.1 2626.08
   291.4 2626.98   299.9 2630.16   308.2 2631.65     317 2631.69   329.3 2631.21
     340  2632.4   348.3 2633.33   380.7 2637.97   399.5 2642.09   411.1 2645.35
#Mann= 5 ,-1,0
       0     .05       0   160.6     .07       0   177.6    .045       0
  192.19     .07       0     340      .1       0
Bank Sta=177.6,192.19
XS Rating Curve= 0 ,0
Exp/Cntr(USF)=0,0
Exp/Cntr=0.3,0.1

Type RM Length L Ch R = 1 ,2022    ,109.2,109.8,109.8
XS GIS Cut Line= 2
2307396.08501849528313.6326567562307692.64693215528593.342751882
#Sta/Elev= 30
       0 2632.11    22.1  2630.9    75.1 2629.66   104.6 2628.24   121.1  2627.9
   137.6 2626.07   143.1 2625.83   165.1 2625.67   169.5 2625.24   174.2 2622.74
   176.1  2621.9   180.8 2621.58  186.922622.559   192.6 2623.74     215 2624.88
   264.1 2623.86   269.5 2623.97   280.5 2624.88   303.4 2624.44   331.6 2624.93
   337.5 2625.33   353.4 2627.28   368.5 2628.08   376.1 2628.82   379.5 2629.33
   389.9 2631.98     396 2634.67   398.7 2635.32   404.4  2635.5   407.7 2635.99
#Mann= 6 ,-1,0
       0      .1       0      70     .05       0   174.2    .045       0
  186.92     .05       0     190     .07       0     360      .1       0
#XS Ineff= 2 , 0
          159.42 2629.58  291.47         2629.67
Permanent Ineff=
       F       F
Bank Sta=174.2,186.92
XS Rating Curve= 0 ,0
Exp/Cntr(USF)=0,0
Exp/Cntr=0.3,0.1

Type RM Length L Ch R = 1 ,1912    ,373,374,369.3
XS GIS Cut Line= 2
2307313.53019149528349.6235139492307610.16898105528663.078177861
#Sta/Elev= 30
       0 2632.49    12.9 2630.85    32.4 2629.84    67.9 2629.23   131.6 2626.93
   151.5 2627.43   171.3 2628.57   184.2 2629.34   219.2 2630.07   222.3 2629.06
     225 2627.32   227.9 2624.46   230.7 2622.31  231.952622.033   233.6 2621.65
   236.6  2621.4   241.7 2622.06   244.9 2622.92   253.4  2623.7   265.7 2623.21
   290.2 2623.07   296.8 2623.03   306.5  2622.1   318.1 2622.68   324.3 2624.22
   358.8 2623.89   400.5 2625.17   405.4 2625.62   411.8 2626.68   431.6 2630.65
#Mann= 7 ,-1,0
       0      .1       0    32.4     .05       0   171.3      .1       0
  231.95    .045       0   241.7      .1       0   290.2     .07       0
   431.6      .1       0
Bank Sta=231.95,241.7
XS Rating Curve= 0 ,0
Exp/Cntr(USF)=0,0
Exp/Cntr=0.3,0.1

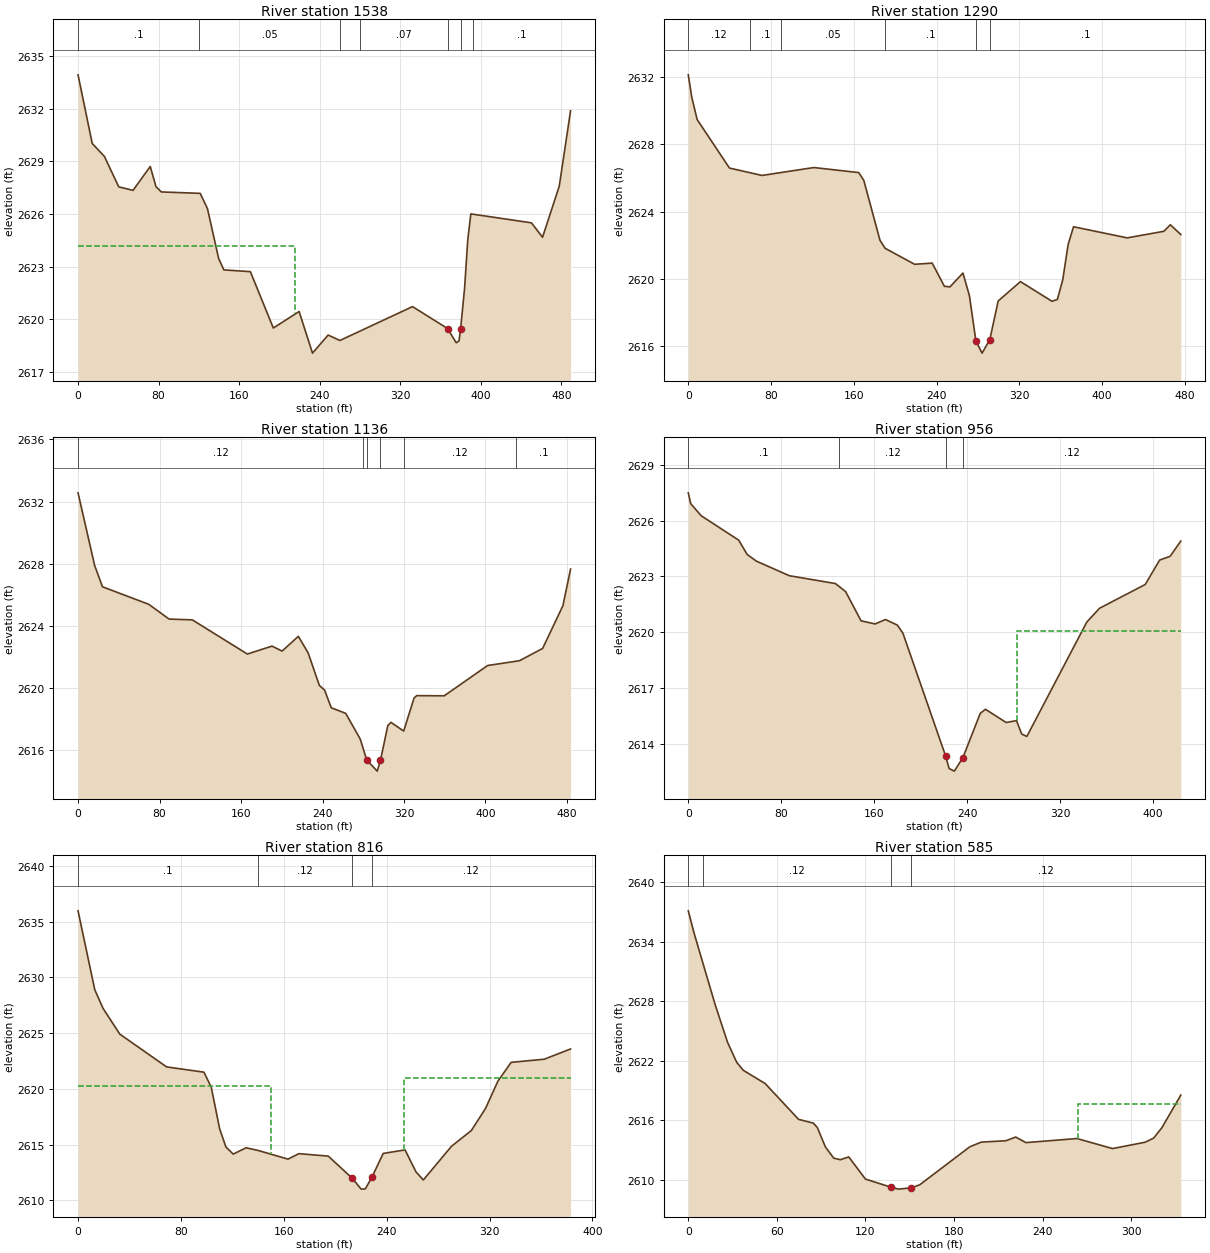
Type RM Length L Ch R = 1 ,1538    ,249.9,248.8,250.6
XS GIS Cut Line= 3
 2307159.2323726528457.2452514822307363.71113499528706.411425519
2307484.23173004528821.515364613
#Sta/Elev= 30
       0 2633.93    14.1 2630.02    26.2 2629.28    40.4 2627.55    54.6 2627.35
    71.7 2628.71    77.4 2627.56    82.7 2627.26   121.3 2627.18   128.5 2626.31
   139.6 2623.47   144.8 2622.82   171.1 2622.72   193.9 2619.51   219.5 2620.45
   232.8 2618.08   248.3 2619.11     260  2618.8   332.1 2620.73   366.9 2619.48
   375.5 2618.67   378.3 2618.78  379.85 2619.47   383.8 2621.78   386.9  2624.5
     390 2626.01   450.2  2625.5   461.2 2624.68   477.8 2627.59     489 2631.88
#Mann= 7 ,-1,0
       0      .1       0     120     .05       0     260      .1       0
     280     .07       0   366.9    .045       0  379.85     .07       0
  392.33      .1       0
#XS Ineff= 2 , 0
          215.25 2624.16
Permanent Ineff=
       F       F
Bank Sta=366.9,379.85
XS Rating Curve= 0 ,0
Exp/Cntr(USF)=0,0
Exp/Cntr=0.3,0.1

Type RM Length L Ch R = 1 ,1290    ,153.2,153.3,153.3
XS GIS Cut Line= 2
2307078.65961523528510.5993126612307382.66943084528877.036088175
#Sta/Elev= 30
       0 2632.13     3.4 2630.79     8.6 2629.47    39.8 2626.59    71.3 2626.15
   121.4 2626.62   164.8 2626.32   169.7 2625.85   185.3  2622.3   190.3 2621.82
   218.8 2620.87   235.8 2620.94   247.6 2619.56     253 2619.53   265.5 2620.35
   271.8    2619     278 2616.32     284 2615.59  291.422616.379   299.6 2618.69
   321.1 2619.84   351.6 2618.67   356.8 2618.78     362 2619.95   367.2 2622.04
   372.4  2623.1   424.3 2622.44   459.7 2622.83     466 2623.22   476.1 2622.64
#Mann= 6 ,-1,0
       0     .12       0      60      .1       0      90     .05       0
     190      .1       0     278    .045       0  291.42      .1       0
Bank Sta=278,291.42
XS Rating Curve= 0 ,0
Exp/Cntr(USF)=0,0
Exp/Cntr=0.3,0.1

Type RM Length L Ch R = 1 ,1136    ,176.4,179.9,181.7
XS GIS Cut Line= 2
2306961.84976591528605.6806904512307267.74036483528980.182264831
#Sta/Elev= 30
       0 2632.56    16.3 2627.88      24 2626.51    69.5 2625.38    89.4 2624.43
   112.2 2624.38   166.2 2622.18   190.4 2622.69   200.3 2622.37   216.3 2623.32
   225.9 2622.25   236.9 2620.16   242.1 2619.85   248.6 2618.72   262.8 2618.36
     277 2616.71   283.4 2615.36   293.7 2614.64   296.9 2615.33   304.1 2617.57
   307.2 2617.78   319.7 2617.22   329.9 2619.35   332.5  2619.5   359.5 2619.49
   402.1 2621.44   433.4 2621.75   456.1 2622.54     476 2625.29   483.5 2627.65
#Mann= 6 ,-1,0
       0     .12       0     280      .1       0   283.4    .045       0
   296.9      .1       0     320     .12       0     430      .1       0
Bank Sta=283.4,296.9
XS Rating Curve= 0 ,0
Exp/Cntr(USF)=0,0
Exp/Cntr=0.3,0.1

Type RM Length L Ch R = 1 ,956     ,142.5,140.2,136.9
XS GIS Cut Line= 3
2306850.67612838528729.2982210712306945.73844043528824.360533122
2307073.70693743529083.953769878
#Sta/Elev= 30
       0 2627.49     2.1 2626.91    11.1 2626.26    43.4 2624.95    50.7 2624.18
    58.7 2623.82      87 2623.04   126.6 2622.62   135.4 2622.19   148.7 2620.62
   160.8 2620.45   169.7 2620.69   179.9 2620.39   184.7 2619.96   221.4 2613.38
   224.5 2612.69     229 2612.55   236.4 2613.28   251.3 2615.65   255.8 2615.87
   273.6 2615.16   282.5 2615.26     287 2614.54   291.4 2614.41     343 2620.55
   353.9 2621.29   393.3 2622.57   405.7 2623.88   414.7 2624.08   423.9  2624.9
#Mann= 4 ,-1,0
       0      .1       0     130     .12       0   221.4    .045       0
   236.4     .12       0
#XS Ineff= 2 , 0
                          282.61         2620.07
Permanent Ineff=
       F       F
Bank Sta=221.4,236.4
XS Rating Curve= 0 ,0
Exp/Cntr(USF)=0,0
Exp/Cntr=0.3,0.1

Type RM Length L Ch R = 1 ,816     ,231.4,231.7,230
XS GIS Cut Line= 2
2306751.95757356528831.6730186652306993.26959646529129.047430723
#Sta/Elev= 30
       0 2635.97      13  2628.9    19.4 2627.23    32.5 2624.91    68.9 2621.97
    97.9  2621.5   103.6 2620.15   110.1 2616.43     115 2614.79   120.7 2614.15
   130.7 2614.72     140 2614.48   163.3  2613.7   171.7 2614.19   194.6 2613.97
   213.1    2612   220.2 2611.01   223.4 2611.03   228.6 2612.09   237.3 2614.21
   254.3 2614.53   262.8 2612.56   268.5 2611.83   290.4 2614.85   305.9 2616.27
   316.9 2618.25   326.5 2620.69   336.8 2622.38   362.5 2622.66     383 2623.58
#Mann= 4 ,-1,0
       0      .1       0     140     .12       0   213.1    .045       0
   228.6     .12       0
#XS Ineff= 2 , 0
       0     150 2620.25  253.16       0 2620.98
Permanent Ineff=
       F       F
Bank Sta=213.1,228.6
XS Rating Curve= 0 ,0
Exp/Cntr(USF)=0,0
Exp/Cntr=0.3,0.1

Type RM Length L Ch R = 1 ,585     ,144.8,145.8,146.6
XS GIS Cut Line= 2
2306637.39530006529002.2976813212306868.95734224 529242.39095663
#Sta/Elev= 30
       0 2637.09       4 2634.81    18.1  2627.7    26.6 2623.86    32.8 2621.85
    37.3 2621.04    52.1 2619.71    74.7 2616.11    84.7 2615.73    87.4 2615.29
    92.9 2613.33    98.5 2612.21     103 2612.05   108.7 2612.33     120  2610.1
   137.4 2609.28   142.3 2609.09   151.1 2609.22   156.8 2609.53   190.7 2613.35
   198.5 2613.82   215.2 2613.96   221.8 2614.33   228.7 2613.77   263.3 2614.18
   287.4 2613.17   309.5 2613.81   315.2 2614.22   320.8 2615.27   333.6 2618.55
#Mann= 4 ,-1,0
       0      .1       0      10     .12       0   137.4    .045       0
   151.1     .12       0
#XS Ineff= 2 , 0
                          263.77         2617.63
Permanent Ineff=
       F       F
Bank Sta=137.4,151.1
XS Rating Curve= 0 ,0
Exp/Cntr(USF)=0,0
Exp/Cntr=0.3,0.1

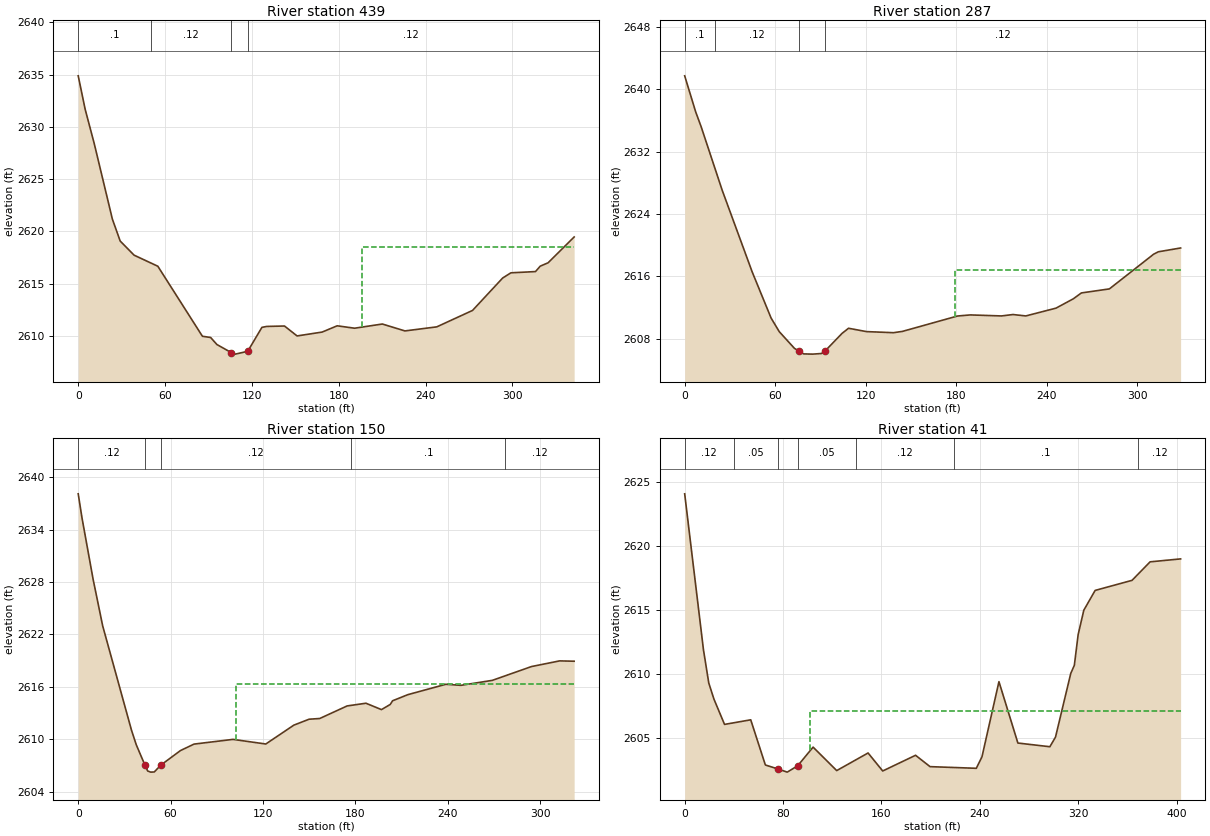
Type RM Length L Ch R = 1 ,439     ,153.4,151.8,150.2
XS GIS Cut Line= 2
 2306553.0878426 529111.430847932306771.69504927529375.237039314
#Sta/Elev= 30
       0 2634.88     4.8 2631.68    11.1 2628.38    23.6 2621.17      29 2619.07
    38.6 2617.72      55 2616.66    85.8 2609.96    91.5 2609.84    95.8 2609.17
   105.7  2608.4   108.5 2608.25   117.1 2608.52   126.9 2610.81   130.2  2610.9
   142.5 2610.94   151.2 2609.99   168.5 2610.36   178.9 2610.96   190.9 2610.73
   210.1 2611.13   225.7 2610.47   247.7 2610.86   272.4 2612.43   293.2 2615.53
   298.9 2616.03   315.9 2616.15   319.2 2616.67   324.6 2616.99   342.6 2619.46
#Mann= 4 ,-1,0
       0      .1       0      50     .12       0   105.7    .045       0
   117.1     .12       0
#XS Ineff= 2 , 0
                          196.14          2618.5
Permanent Ineff=
       F       F
Bank Sta=105.7,117.1
XS Rating Curve= 0 ,0
Exp/Cntr(USF)=0,0
Exp/Cntr=0.3,0.1

Type RM Length L Ch R = 1 ,287     ,127.9,136.8,141.2
XS GIS Cut Line= 2
2306449.70817114529236.2972186782306693.45768922 529456.89053254
#Sta/Elev= 30
       0 2641.71     7.3 2637.08    10.9 2635.19    24.9 2627.01    44.8 2616.52
    57.3 2610.62    62.7 2608.88    72.8 2606.73      76 2606.39    78.8 2606.03
    84.8    2606    90.7 2606.08      93 2606.39   104.3 2608.66   108.6 2609.32
   120.5 2608.89   138.4 2608.75   144.4 2608.92   180.8 2610.89   189.3 2611.03
     210  2610.9   217.6 2611.08   226.1  2610.9   246.1  2611.9   257.6  2613.1
   262.9 2613.85   281.5 2614.37   310.8 2618.82   313.9 2619.13   328.7 2619.62
#Mann= 4 ,-1,0
       0      .1       0      20     .12       0      76    .045       0
      93     .12       0
#XS Ineff= 2 , 0
                          179.23         2616.77
Permanent Ineff=
       F       F
Bank Sta=76,93
XS Rating Curve= 0 ,0
Exp/Cntr(USF)=0,0
Exp/Cntr=0.3,0.1

Type RM Length L Ch R = 1 ,150     ,120.8,109.6,101.9
XS GIS Cut Line= 3
2306382.14682467529294.7996983492306425.85940074 529414.38735566
2306583.73998547529528.199977513
#Sta/Elev= 30
       0 2638.09     2.5 2635.29     9.7 2628.28    15.9 2622.96    34.6 2611.02
    37.7 2609.35   43.38    2607    45.1 2606.35    47.1 2606.22    49.4 2606.24
    53.6 2607.02    66.4 2608.69    75.2 2609.43   100.5 2609.97   121.8 2609.44
     140  2611.6   149.9 2612.28   156.8 2612.36   174.6  2613.8   186.8 2614.11
   196.9 2613.38   202.6 2613.97   204.1 2614.39     214 2615.09   238.7 2616.28
   248.5 2616.16   268.9 2616.73   294.3 2618.31   312.6 2618.96     322 2618.92
#Mann= 5 ,-1,0
       0     .12       0   43.38    .045       0    53.6     .12       0
  177.33      .1       0  277.33     .12       0
#XS Ineff= 2 , 0
                          102.33         2616.35
Permanent Ineff=
       F       F
Bank Sta=43.38,53.6
XS Rating Curve= 0 ,0
Exp/Cntr(USF)=0,0
Exp/Cntr=0.3,0.1

Type RM Length L Ch R = 1 ,41      ,,,
XS GIS Cut Line= 4
2306257.65871156529314.861406575 2306278.3082323529370.046191438
2306385.55802025529423.6710854152306580.55763472529534.577116142
#Sta/Elev= 30
       0  2624.1    15.3 2611.86    19.6 2609.27    23.8 2608.01    32.4 2606.03
    53.7 2606.39    65.6 2602.85   75.73 2602.54    83.4 2602.29    91.9 2602.79
   104.4 2604.25   123.6 2602.41   149.1 2603.79     161 2602.38   187.7 2603.61
   199.5 2602.72   237.1 2602.59   241.7 2603.49   255.5 2609.38   270.9 2604.57
   296.9 2604.28   301.5 2605.04   313.9 2610.03   316.8 2610.66   319.9 2613.07
   324.5 2614.98   333.7 2616.53   363.7 2617.32   378.4 2618.77   403.2    2619
#Mann= 7 ,-1,0
       0     .12       0      40     .05       0   75.73    .045       0
    91.9     .05       0  138.92     .12       0  218.83      .1       0
  368.83     .12       0
#XS Ineff= 2 , 0
                          102.16         2607.07
Permanent Ineff=
       F       F
Bank Sta=75.73,91.9
XS Rating Curve= 0 ,0
Exp/Cntr(USF)=0,0
Exp/Cntr=0.3,0.1
LCMann Table=0

Chan Stop Cuts=-1
Use User Specified Reach Order=0
Composite Channel Slope=5